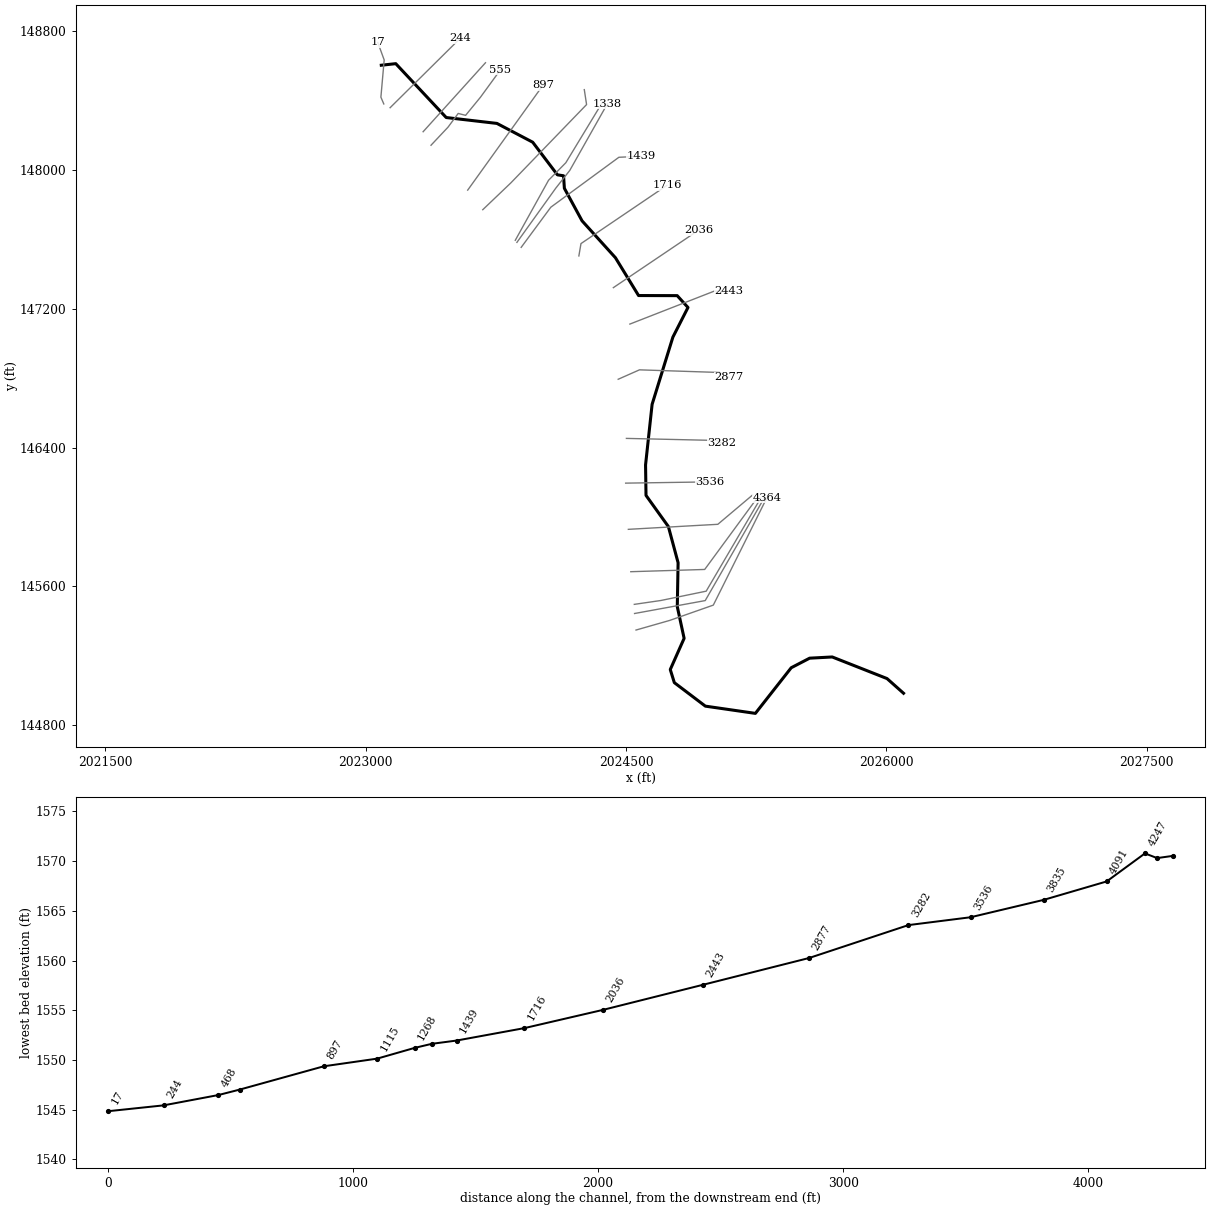
--- RICHCK2_DS.prj (project) ---

Proj Title=RICHCK2_DS
Current Plan=p01
Default Exp/Contr=0,0
English Units
Geom File=g01
Flow File=f01
Plan File=p01
Background Map Layer=Inundation Boundary (01pct Value_0)
Background Map Layer=Inundation Boundary (01pct Value_0)
Background Map Layer=Inundation Boundary (01pct Value_0)
BEGIN DESCRIPTION:
Stream Name: Rich Creek (Lower Reach)
Flood Zone: Approximate
Monroe County, West Virginia
HEC-RAS Version: 5.0.7
Vertical Datum: NAVD88
Projection: NAD 1983 StatePlane West Virginia S FIPS 4702 (US Feet)
LiDAR: 2016, 1-meter
Land Use: 2016 NLCD
Hydrology Method:
Regression.
Model Notes:
Upstream portion(XS 3834) is retained for model accuracy only (the Effective model for the area around the confluence of Rich Creek and Brush Creek is a 2D unsteady model). Tie in occurs at XS 3834, please refer to 2D model for WSELs upstream of this cross section.
END DESCRIPTION:
DSS Export Rating Curves= 0
DSS Export Rating Curve Sorted= 0
DSS Export Volume Flow Curves= 0
DXF OffsetX= 0
DXF OffsetY= 0
DXF ScaleX= 0
DXF ScaleY= 0

--- RICHCK2_DS.p01 (plan) ---

Plan Title=Floodplain
Program Version=5.07
Short Identifier=Floodplain
Geom File=g01
Flow File=f01
Subcritical Flow
K Sum by GR= 0
Std Step Tol= 0.01
Critical Tol= 0.01
Num of Std Step Trials= 20
Max Error Tol= 0.3
Flow Tol Ratio= 0.001
Split Flow NTrial= 30
Split Flow Tol= 0.02
Split Flow Ratio= 0.02
Log Output Level= 0
Friction Slope Method= 1
Unsteady Friction Slope Method= 2
Unsteady Bridges Friction Slope Method= 1
Parabolic Critical Depth
Global Vel Dist= 0 , 0 , 0
Global Log Level= 0
CheckData=True
Encroach Param=-1 ,0,0, 0
Mapping Interval=1HOUR
Computation Time Step Use Courant=        0
Computation Time Step Use Time Series=    0
Computation Time Step Count To Double=0
Computation Time Step Max Doubling=0
Computation Time Step Max Halving=0
Computation Time Step Residence Courant=0
Run HTab= 0
Run UNet= 0
Run Sediment= 0
Run PostProcess= 0
Run WQNet= 0
Run RASMapper= 0
UNET Theta= 0
UNET Theta Warmup= 0
UNET ZTol= 0
UNET ZSATol= 0
UNET MxIter= 0
UNET Max Iter WO Improvement= 0
UNET MaxInSteps= 0
UNET DtIC= 0
UNET DtMin= 0
UNET MaxCRTS= 0
UNET WFStab= 0
UNET SFStab= 0
UNET WFX= 1
UNET SFX= 1
UNET 1D Methodology=Finite Difference
UNET DSS MLevel= 1
UNET Pardiso=0
UNET DZMax Abort= 0
UNET Use Existing IB Tables= 0
UNET Froude Reduction=False
UNET Froude Limit= 0
UNET Froude Power= 0
UNET D1 Cores= 0
UNET D2 Coriolis=0
UNET D2 Cores= 0
UNET D2 Theta= 1
UNET D2 Theta Warmup= 1
UNET D2 Z Tol= 0.01
UNET D2 Volume Tol= 0.01
UNET D2 Max Iterations= 20
UNET D2 Equation= 0
UNET D2 RampUpFraction=0.1
UNET D2 TimeSlices= 1
UNET D2 BCVolumeCheck=0
UNET D1D2 MaxIter= 0
UNET D1D2 ZTol=0.01
UNET D1D2 QTol=0.1
UNET D1D2 MinQTol=1
Write IC File= 0
Write IC File at Fixed DateTime=0
Write IC File at Sim End=0
Echo Input=False
Echo Parameters=False
Echo Output=False
Write Detailed= 0
HDF Write Warmup=0
HDF Write Time Slices=0
HDF Flush=0
HDF Face Node Velocities=0
HDF Compression= 1
HDF Chunk Size= 1
HDF Spatial Parts= 1
HDF Use Max Rows=0
HDF Fixed Rows= 1
Calibration Method= 0
Calibration Iterations= 20
Calibration Max Change=0.05
Calibration Tolerance=0.2
Calibration Maximum=1.5
Calibration Minimum=0.5
Calibration Optimization Method= 1
WQ AD Non Conservative
WQ ULTIMATE=-1
WQ Max Comp Step=1HOUR
WQ Output Interval=15MIN
WQ Output Selected Increments= 0
WQ Output face flow=0
WQ Output face velocity=0
WQ Output face area=0
WQ Output face dispersion=0
WQ Output cell volume=0
WQ Output cell surface area=0
WQ Output cell continuity=0
WQ Output cumulative cell continuity=0
WQ Output face conc=0
WQ Output face dconc_dx=0
WQ Output face courant=0
WQ Output face peclet=0
WQ Output face adv mass=0
WQ Output face disp mass=0
WQ Output cell mass=0
WQ Output cell source sink temp=0
WQ Output nsm pathways=0
WQ Output nsm derived pathways=0
WQ Output MaxMinRange=-1
WQ Daily Max Min Mean=-1
WQ Daily Range=0
WQ Daily Time=0
WQ Create Restart=0
WQ Fixed Restart=0
WQ System Summary=0
WQ Write To DSS=0
WQ Use Fixed Temperature=0
Sorting and Armoring Iterations= 10
XS Update Threshold= 0.02
Bed Roughness Predictor= 0
Hydraulics Update Threshold= 0.02
Energy Slope Method= 1
Volume Change Method= 1
Sediment Retention Method= 0
XS Weighting Method= 0
Number of US Weighted Cross Sections= 1
Number of DS Weighted Cross Sections= 1
Upstream XS Weight=0
Main XS Weight=1
Downstream XS Weight=0
Number of DS XS's Weighted with US Boundary= 1
Upstream Boundary Weight= 1
Weight of XSs Associated with US Boundary= 0
Number of US XS's Weighted with DS Boundary= 1
Downstream Boundary Weight= 0.5
Weight of XSs Associated with DS Boundary= 0.5
Percentile Method= 0
Sediment Output Level= 3
Mass or Volume Output= 0
Output Increment Type= 1
Profile and TS Output Increment= 1
XS Output Flag= 0
XS Output Increment= 10
Write Gradation File= 0
Read Gradation Hotstart= 0
Write HDF5 File= 1
Write Binary Output= 1
Write DSS Sediment File= 0
SV Curve= 0
Specific Gage Flag= 0

--- RICHCK2_DS.f01 (steady flow) ---

Flow Title=Flow
Program Version=5.07
Number of Profiles= 6
Profile Names=01pct,10pct,04pct,02pct,0_2pct,01plus
River Rch & RM=Rich Cr (Lower),Main            ,4364
    6910    4020    5100    5980    9210   10200
Boundary for River Rch & Prof#=Rich Cr (Lower),Main            , 1
Up Type= 0
Dn Type= 3
Dn Slope=0.00258
Boundary for River Rch & Prof#=Rich Cr (Lower),Main            , 2
Up Type= 0
Dn Type= 3
Dn Slope=0.00258
Boundary for River Rch & Prof#=Rich Cr (Lower),Main            , 3
Up Type= 0
Dn Type= 3
Dn Slope=0.00258
Boundary for River Rch & Prof#=Rich Cr (Lower),Main            , 4
Up Type= 0
Dn Type= 3
Dn Slope=0.00258
Boundary for River Rch & Prof#=Rich Cr (Lower),Main            , 5
Up Type= 0
Dn Type= 3
Dn Slope=0.00258
Boundary for River Rch & Prof#=Rich Cr (Lower),Main            , 6
Up Type= 0
Dn Type= 3
Dn Slope=0.00258
DSS Import GetInterval= 0
DSS Import GetPeak= 0
DSS Import FillOption= 0

--- RICHCK2_DS.g01 (geometry) ---

Geom Title=Geometry
Program Version=5.07

River Reach=Rich Cr (Lower) ,Main
Reach XY= 30
2026098.95889044144984.373002619     2026003.896 145068.95100002
     2025688.086145193.4600000082025557.87800002145186.515000001
2025451.81299999 145131.451000022025245.21600002144868.431000009
     2024957.021144910.0970000032024778.20200002145045.513999999
2024754.76400003145121.035000011     2024834.625145300.722000018
2024795.23500001145483.3560000212024799.90300003145736.486000001
     2024743.914145944.819999993     2024615.007146124.506999999
2024612.40300003146300.2880000172024650.16400003146649.246999994
2024769.85699999147036.5150000152024856.83600003147207.348000005
2024794.69499999 147275.549000012024572.11399999 147276.09800002
2024438.86700001147493.9800000192024246.51799998147706.538000017
2024144.59599999147894.154000014     2024139.822147966.202999994
2024104.23200002147971.8450000142023962.14300001148159.663000003
2023755.89300004148267.9970000092023463.70500004148301.851000011
2023172.98199999148612.296000019     2023089.648148603.269000009

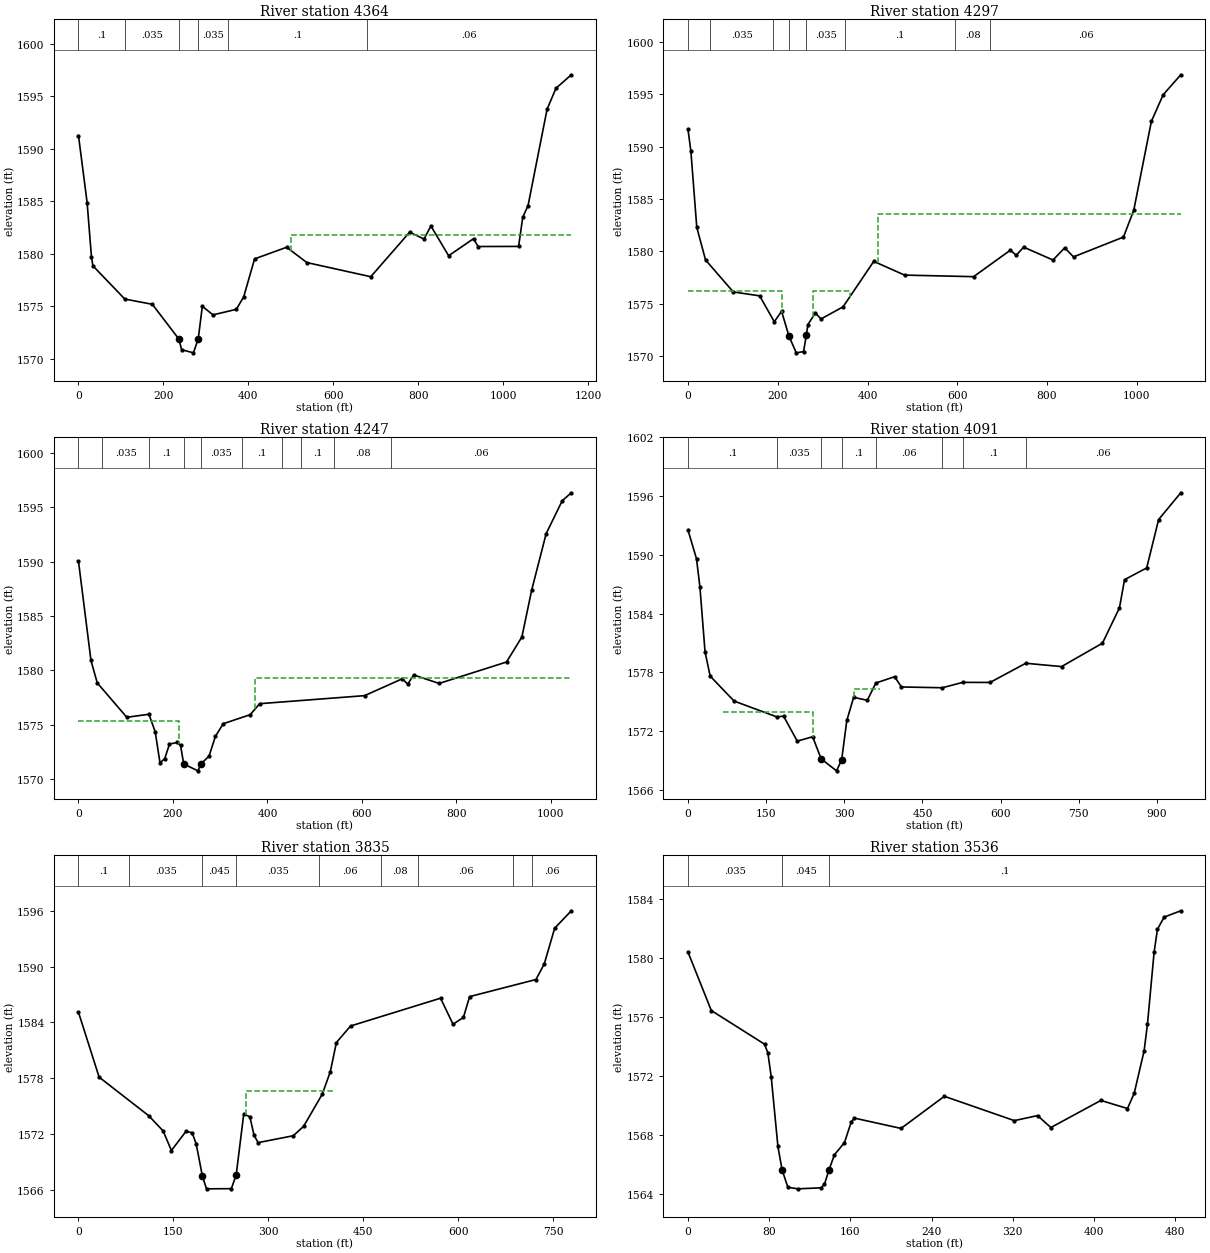
Type RM Length L Ch R = 1 ,4364    ,71.1,66.5,62.4
XS GIS Cut Line= 4
2024557.44012903145348.6356540912024751.75744605145404.154887527
2025002.80093637 145492.261497112025311.77753984146111.421643905
#Sta/Elev= 30
       0 1591.26    20.3 1584.87    30.5 1579.69    33.9 1578.84     109 1575.67
   173.8 1575.17   236.31571.854   242.8 1570.84   270.6 1570.54  281.94 1571.89
   291.5 1574.98   316.7 1574.16   371.5 1574.69   388.9 1575.88   414.5  1579.5
     490 1580.61   537.6 1579.15     688  1577.8   779.6 1582.05   813.4 1581.39
   829.6 1582.64   871.3  1579.8     930 1581.43   940.6 1580.68    1036 1580.69
  1045.8 1583.46  1058.3 1584.59  1103.1 1593.78    1124 1595.77  1160.1 1597.06
#Mann= 6 ,-1 , 0
       0      .1       0     110    .035       0   236.3    .045       0
  281.94    .035       0  352.09      .1       0  678.15     .06       0
#XS Ineff= 2 , 0
                          500.34         1581.74
Permanent Ineff=
       F       F
Bank Sta=236.3,281.94
XS Rating Curve= 0 ,0
Exp/Cntr(USF)=0,0
Exp/Cntr=0.5,0.3

Type RM Length L Ch R = 1 ,4297    ,48.2,49.8,50
XS GIS Cut Line= 3
     2024549.098      145443.911     2024956.259      145518.392
     2025297.069      146111.377
#Sta/Elev= 30
       0 1591.65     6.5 1589.56    19.6  1582.3    39.1 1579.18     101 1576.12
   159.7 1575.75   192.3 1573.28   208.6 1574.27   224.9 1571.92   241.2 1570.31
   257.5 1570.43     264 1572.06   267.2 1573.01   283.6  1574.1   296.6 1573.55
   345.5  1574.7   413.9 1579.04   482.6 1577.73   636.4 1577.58   718.3 1580.11
   731.4 1579.62   747.7  1580.4   813.2 1579.17   839.3 1580.33     859 1579.47
   970.2 1581.36   993.1 1583.91  1032.4  1592.4  1058.6 1594.94  1097.9 1596.85
#Mann= 8 ,-1 , 0
       0      .1       0      50    .035       0     190      .1       0
   224.9    .045       0     264    .035       0     350      .1       0
  593.92     .08       0  673.92     .06       0
#XS Ineff= 3 ,-1
       0  209.74 1576.23  278.51  361.03 1576.23  422.63  1097.9 1583.52
Permanent Ineff=
       F       F       F
Bank Sta=224.9,264
XS Rating Curve= 0 ,0
Exp/Cntr=0.5,0.3

Type RM Length L Ch R = 1 ,4247    ,162.3,156.2,153
XS GIS Cut Line= 4
2024547.52298538145496.6025873782024700.99805365145518.953325476
2024961.75666479145572.5950969112025276.15704737146109.012811263
#Sta/Elev= 30
       0 1590.03    26.4 1580.92    39.7 1578.86   102.2  1575.7   149.1 1575.98
   162.4 1574.36   172.5 1571.52   182.5  1571.9   192.6 1573.24   209.3 1573.39
     216 1573.12   222.7 1571.41   252.8 1570.78   259.5 1571.43   276.3 1572.13
   289.7 1573.94   306.4 1575.11   363.4 1575.94   383.5 1576.95   605.6 1577.69
   685.4 1579.24   696.9 1578.74   709.4 1579.59   763.3 1578.81     906 1580.78
   938.5 1583.08   959.3  1587.4   989.9 1592.58  1023.9  1595.6  1043.1 1596.33
#Mann= 10 ,-1 , 0
       0      .1       0      50    .035       0     150      .1       0
   222.7    .045       0   259.5    .035       0  345.09      .1       0
  431.31    .035       0  471.31      .1       0  541.31     .08       0
  661.31     .06       0
#XS Ineff= 2 , 0
             213 1575.34  373.07         1579.34
Permanent Ineff=
       F       F
Bank Sta=222.7,259.5
XS Rating Curve= 0 ,0
Exp/Cntr(USF)=0,0
Exp/Cntr=0.5,0.3

Type RM Length L Ch R = 1 ,4091    ,259.5,256.4,257.2
XS GIS Cut Line= 3
     2024527.397      145684.797     2024953.227       145697.73
      2025260.61      146116.585
#Sta/Elev= 30
       0 1592.54    16.4  1589.6    22.9 1586.74    32.8 1580.09    42.6 1577.63
    88.5 1575.08   170.4 1573.47   183.5 1573.54   209.7 1570.99   239.2 1571.44
   255.6 1569.18   285.1 1567.96   294.9 1569.08   304.8  1573.1   317.9 1575.46
   344.1 1575.16   360.5 1576.92   396.5 1577.57   409.6 1576.52   488.1 1576.44
   527.3 1576.99   579.6 1576.98   648.2 1578.94   716.8  1578.6   795.3 1580.99
   827.9 1584.59   837.7 1587.47   880.2 1588.67   903.1 1593.61   945.6 1596.34
#Mann= 8 ,-1 , 0
       0      .1       0   170.4    .035       0   255.6    .045       0
   294.9      .1       0   360.5     .06       0   488.1     .08       0
   527.3      .1       0   648.2     .06       0
#XS Ineff= 2 ,-1
   67.34  239.26 1573.96  318.05  368.19 1576.36
Permanent Ineff=
       F       F
Bank Sta=255.6,294.9
XS Rating Curve= 0 ,0
Exp/Cntr=0.3,0.1

Type RM Length L Ch R = 1 ,3835    ,292,298.5,292.7
XS GIS Cut Line= 4
     2024513.291      145928.937     2024900.996      145950.808
     2025028.831      145957.874      2025229.36      146127.002
#Sta/Elev= 30
       0 1585.09    32.6 1578.12     111 1573.97   133.8 1572.33   146.8 1570.23
   169.7 1572.28   179.5 1572.15     186 1570.94   195.8 1567.47   202.3 1566.11
   241.5 1566.13  249.18  1567.6   261.1 1574.16   270.8 1573.86   277.4 1571.86
   283.9 1571.08   339.4 1571.82   355.7 1572.83   385.1 1576.28   397.9  1578.7
   407.5 1581.84   429.9 1583.62   572.1 1586.61   591.8 1583.81   608.2 1584.54
     618 1586.78   722.9 1588.62     736  1590.3   752.4 1594.13   778.7 1596.01
#Mann= 9 ,-1 , 0
       0      .1       0      80    .035       0   195.8    .045       0
  249.18    .035       0     380     .06       0  478.32     .08       0
  536.35     .06       0  686.35     .08       0  716.35     .06       0
#XS Ineff= 1 ,-1
  264.76  403.441576.584
Permanent Ineff=
       F
Bank Sta=195.8,249.18
XS Rating Curve= 0 ,0
Exp/Cntr=0.3,0.1

Type RM Length L Ch R = 1 ,3536    ,254.7,253.8,252.6
XS GIS Cut Line= 2
     2024497.708      146195.148     2024983.126      146202.375
#Sta/Elev= 30
       0 1580.43      23 1576.46    75.4 1574.18    78.7 1573.59      82 1571.97
    88.6 1567.24   92.71 1565.65    98.4 1564.47   108.2 1564.36   131.2 1564.43
   134.5 1564.68     139 1565.66   144.3 1566.67   154.2  1567.5   160.7 1568.87
     164 1569.16   209.9 1568.46   252.6 1570.64   321.5 1568.99   344.4 1569.33
   357.5 1568.52   406.8 1570.36     433 1569.81   439.6 1570.84   449.4 1573.73
   452.7 1575.55   459.2  1580.4   462.5 1581.97   469.1  1582.8   485.5 1583.23
#Mann= 3 ,-1 , 0
       0    .035       0   92.71    .045       0     139      .1       0
Bank Sta=92.71,139
XS Rating Curve= 0 ,0
Exp/Cntr=0.3,0.1

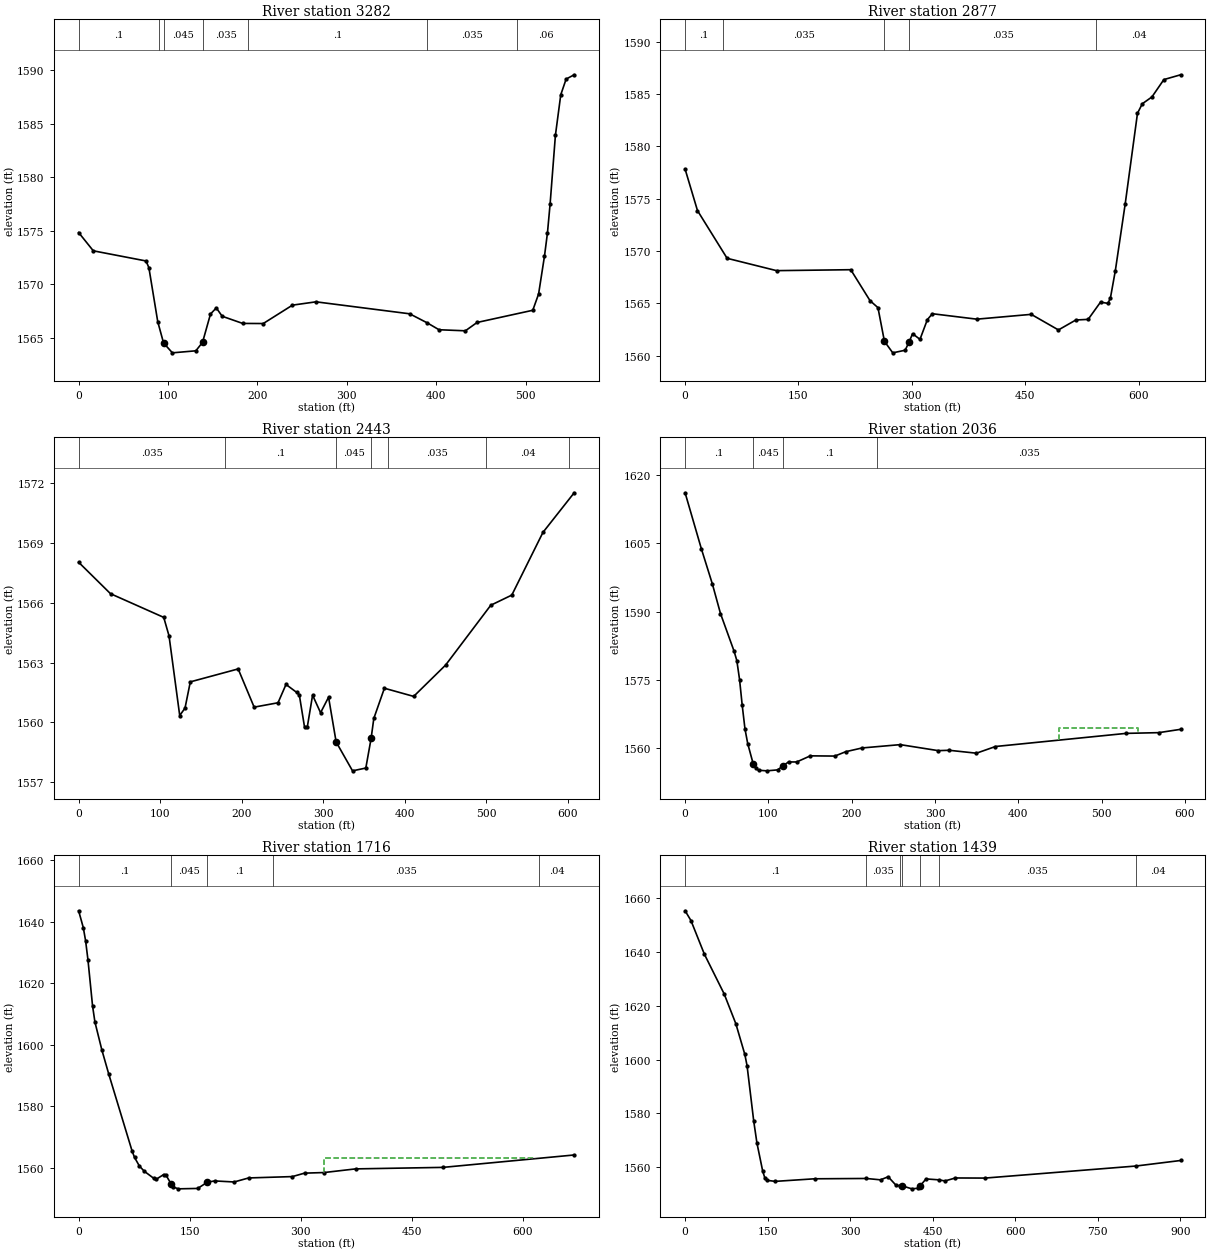
Type RM Length L Ch R = 1 ,3282    ,410.3,405.3,407.1
XS GIS Cut Line= 3
     2024502.048      146452.961      2025026.27      146440.938
     2025051.486      146424.814
#Sta/Elev= 30
       0 1574.82    16.4 1573.11    75.4 1572.16    78.6 1571.53    88.5 1566.48
      95 1564.49   104.9 1563.57   131.1 1563.76   138.6 1564.55   147.5  1567.2
     154 1567.77   160.6 1566.99   183.5 1566.32   206.5 1566.31   239.2 1568.03
   265.5 1568.34   370.3 1567.22     390 1566.37   403.1 1565.73   432.6 1565.63
   445.7 1566.41     508 1567.55   514.5 1569.07   521.1 1572.62   524.4 1574.77
   527.4 1577.51   533.3  1583.9   539.3  1587.7   545.3 1589.17   554.3 1589.57
#Mann= 7 ,-1 , 0
       0      .1       0      90    .035       0      95    .045       0
   138.6    .035       0     190      .1       0     390    .035       0
     490     .06       0
Bank Sta=95,138.6
XS Rating Curve= 0 ,0
Exp/Cntr=0.3,0.1

Type RM Length L Ch R = 1 ,2877    ,412,433.9,435.3
XS GIS Cut Line= 4
     2024454.697      146793.738      2024577.31      146847.991
     2025038.465        146832.8     2025091.633      146804.588
#Sta/Elev= 30
       0 1577.83    16.4 1573.86    55.6  1569.3     121 1568.12   219.2 1568.21
   244.7 1565.25   255.2 1564.58  263.75 1561.36   274.8 1560.26   291.2 1560.51
  296.57 1561.33     301 1562.09   310.8 1561.55   320.6 1563.44   327.2    1564
     386 1563.48     458 1563.94     494 1562.45     517  1563.4   533.3 1563.46
   549.7 1565.11   559.5 1564.99   562.8 1565.51   569.3 1568.12   582.4 1574.53
   598.6 1583.17     605 1584.08   617.7 1584.73   633.5 1586.39   655.7 1586.85
#Mann= 5 ,-1 , 0
       0      .1       0      50    .035       0  263.75    .045       0
  296.57    .035       0  544.08     .04       0
Bank Sta=263.75,296.57
XS Rating Curve= 0 ,0
Exp/Cntr=0.3,0.1

Type RM Length L Ch R = 1 ,2443    ,387.9,407.4,402.8
XS GIS Cut Line= 3
     2024521.972      147111.663     2025008.083       147301.55
     2025094.062      147301.919
#Sta/Elev= 30
       0 1568.04    39.1 1566.46   104.4 1565.27   110.9 1564.34     124 1560.34
   130.5 1560.71     137 1562.03   195.7 1562.68   215.3 1560.76   244.6 1560.98
   254.4  1561.9   267.5  1561.5   270.7 1561.38   277.2 1559.74   280.5 1559.76
     287 1561.36   296.8 1560.48   306.6 1561.26   315.9 1559.01     336 1557.56
   352.3  1557.7   358.8 1559.19   362.1 1560.19   375.1 1561.71     411  1561.3
   450.1 1562.87   505.6 1565.88   531.4 1566.39   569.6 1569.54   607.9 1571.53
#Mann= 7 ,-1 , 0
       0    .035       0     180      .1       0   315.9    .045       0
   358.8      .1       0     380    .035       0     500     .04       0
  601.88     .06       0
Bank Sta=315.9,358.8
XS Rating Curve= 0 ,0
Exp/Cntr=0.3,0.1

Type RM Length L Ch R = 1 ,2036    ,321.8,319.9,320
XS GIS Cut Line= 2
      2024426.84      147321.606     2024920.192      147654.198
#Sta/Elev= 30
       0 1616.05    19.6 1603.72    32.7 1596.07    42.5 1589.55    58.8  1581.3
    62.1 1579.24    65.4 1575.07    68.6 1569.38    71.9 1564.23    75.2 1561.01
    81.7 1556.62      85 1555.57    88.3 1555.17    98.1 1555.04   111.2 1555.25
   117.4 1556.14   124.2 1556.99     134 1556.99   150.4 1558.33   179.8 1558.28
   192.9 1559.24   212.5 1560.06   258.3 1560.79     304 1559.47   317.1 1559.55
   349.8 1558.91   372.7 1560.38   529.6 1563.26   568.8 1563.42     595 1564.15
#Mann= 4 ,-1 , 0
       0      .1       0    81.7    .045       0   117.4      .1       0
     230    .035       0
#XS Ineff= 1 ,-1
  448.71  543.27 1564.53
Permanent Ineff=
       F
Bank Sta=81.7,117.4
XS Rating Curve= 0 ,0
Exp/Cntr=0.3,0.1

Type RM Length L Ch R = 1 ,1716    ,277,276.6,277.1
XS GIS Cut Line= 3
      2024228.12      147504.299     2024240.273      147575.479
     2024734.645      147910.274
#Sta/Elev= 30
       0 1643.54     6.3 1638.06     9.4 1633.82    12.6 1627.59    18.8 1612.65
      22 1607.41    31.4  1598.3    40.8  1590.4    72.2  1565.5    75.5 1563.42
      82 1560.64    88.6 1558.94   101.7 1556.58     105 1556.35   114.9 1557.86
   118.1 1557.61   124.7 1554.89     128 1553.82   134.5 1553.21   160.8 1553.34
   173.9 1555.38   183.8 1555.78     210 1555.44   229.7 1556.75   288.7 1557.19
   305.1 1558.31   331.4  1558.5     374 1559.69   492.1 1560.18   669.3 1564.21
#Mann= 5 ,-1 , 0
       0      .1       0   124.7    .045       0   173.9      .1       0
  262.21    .035       0  622.21     .04       0
#XS Ineff= 1 ,-1
  331.02  615.76 1563.09
Permanent Ineff=
       F
Bank Sta=124.7,173.9
XS Rating Curve= 0 ,0
Exp/Cntr=0.3,0.1

Type RM Length L Ch R = 1 ,1439    ,77.6,101.1,106.4
XS GIS Cut Line= 4
     2023895.726      147553.7622024066.54085768147785.174320528
     2024458.691      148072.848     2024584.906       148078.46
#Sta/Elev= 30
       01655.367  10.6051651.747  35.0721639.208  70.9261624.472  92.1611613.388
 108.4721601.994  112.551597.801 124.7841577.002  130.551568.964 141.0951558.446
 145.1731555.849 149.2511555.115 163.6961554.736 235.1521555.695 329.0141555.814
 355.0371555.308 368.9151556.451 383.5191553.228 390.0391553.195 394.7341553.049
 412.0021551.959 422.8991552.185 426.6611552.992 437.7541555.648 460.4531555.315
 472.1891554.895 490.9661556.001  544.951555.961 819.3261560.447 900.3191562.501
#Mann= 7 ,-1 , 0
       0      .1       0 329.014    .035       0 390.039      .1       0
 394.734    .045       0 426.661      .1       0 460.453    .035       0
 819.326     .04       0
Bank Sta=394.734,426.661
XS Rating Curve= 0 ,0
Exp/Cntr=0.5,0.3

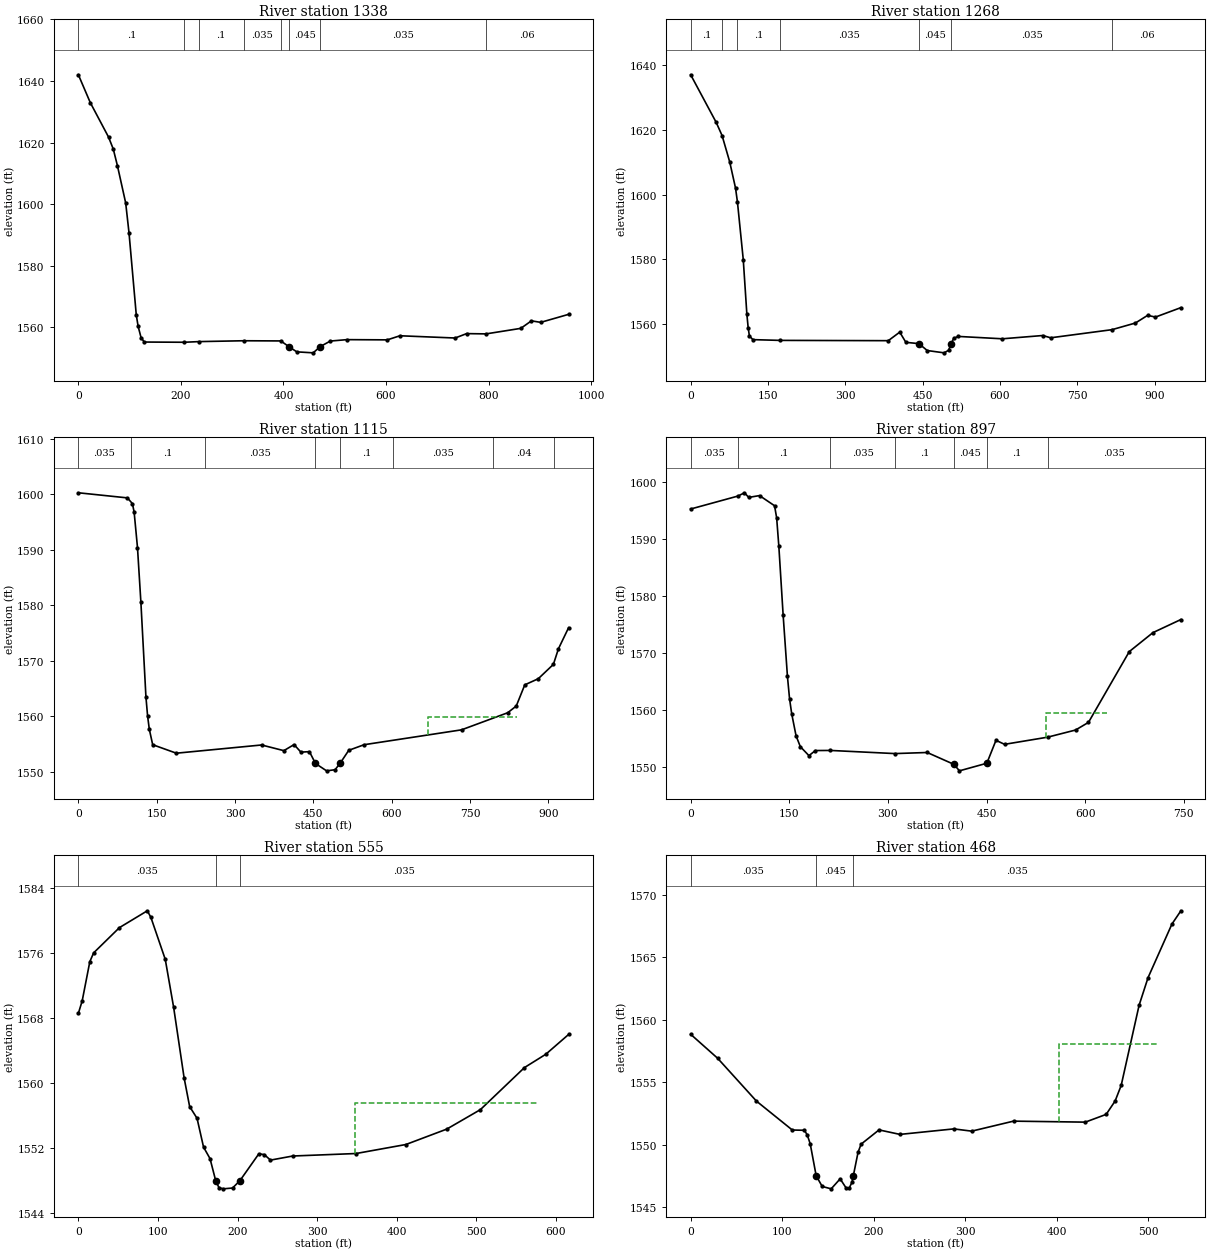
Type RM Length L Ch R = 1 ,1338    ,65.3,70.2,60.2
XS GIS Cut Line= 4
2023871.10254115147582.4231491112024095.05693689147894.886467721
2024175.51959404147996.8058334482024392.76876835148381.685543496
#Sta/Elev= 30
       0 1642.02    23.3 1632.95    58.8 1621.79    68.1 1617.87    76.1 1612.52
    92.3 1600.35    98.8 1590.62   112.9 1564.05   116.5 1560.29   122.3 1556.57
   128.6 1555.14   206.9 1555.07   235.1 1555.28   322.4 1555.56   394.9  1555.5
   410.81553.618   426.1 1551.95     458 1551.63     472 1553.69   491.5 1555.46
   523.7 1555.92   602.6 1555.85   627.3 1557.18   734.9 1556.45   757.3 1557.88
   795.2 1557.79     863 1559.59   883.7 1562.03   901.8 1561.54   956.2 1564.14
#Mann= 8 ,-1 , 0
       0      .1       0   206.9    .035       0   235.1      .1       0
   322.4    .035       0   394.9      .1       0   410.8    .045       0
     472    .035       0   795.2     .06       0
#XS Ineff= 2 , 0
             400 1553.52     482         1553.52
Permanent Ineff=
       F       F
Bank Sta=410.8,472
XS Rating Curve= 0 ,0
Exp/Cntr(USF)=0,0
Exp/Cntr=0.5,0.3

Type RM Length L Ch R = 1 ,1268    ,153,152.8,148.5
XS GIS Cut Line= 4
2023861.71523114147594.4925476842024053.48456402147940.481973441
2024152.72184118148041.0602948822024367.28892692148395.095986354
#Sta/Elev= 30
       0 1636.95    49.5 1622.27    60.9 1618.21    75.7  1610.1      87 1602.01
    90.7 1597.75     102 1579.96     109  1563.1   111.5    1559   113.9 1556.43
   120.7 1555.29   173.2 1555.06   383.3 1554.97   405.5  1557.6   417.4 1554.46
   442.6 1554.06   458.9 1551.93   491.6 1551.22   500.3 1552.02   505.3 1554.05
   510.2 1555.71   519.2 1556.28   604.6 1555.55   682.9 1556.56   698.3 1555.86
   817.1 1558.36   862.6 1560.41   886.3 1562.77   901.6 1562.25   950.9 1565.16
#Mann= 7 ,-1 , 0
       0      .1       0    60.9    .035       0    90.7      .1       0
   173.2    .035       0   442.6    .045       0   505.3    .035       0
   817.1     .06       0
#XS Ineff= 2 , 0
             437 1553.52     510         1553.52
Permanent Ineff=
       F       F
Bank Sta=442.6,505.3
XS Rating Curve= 0 ,0
Exp/Cntr(USF)=0,0
Exp/Cntr=0.5,0.3

Type RM Length L Ch R = 1 ,1115    ,212.6,217.8,220.9
XS GIS Cut Line= 4
     2023674.372      147770.776     2023835.817      147924.901
      2024272.54      148376.523      2024259.37      148462.632
#Sta/Elev= 30
       0 1600.26    93.8 1599.34   103.5 1598.31   106.8 1596.76   113.2 1590.39
   119.7 1580.54   129.4 1563.41   132.6 1559.98   135.9  1557.6   142.3 1554.85
   187.6 1553.32   350.8  1554.8   393.4 1553.78     413 1554.87   426.1 1553.51
   442.4  1553.6  453.97 1551.47   475.2 1550.14   491.5 1550.34   501.3 1551.52
   517.7 1553.84   547.1 1554.85   733.6 1557.53     822 1560.61   838.4 1561.82
   854.7 1565.64   880.5 1566.74   909.5 1569.33   919.2 1572.15   938.6 1575.94
#Mann= 8 ,-1 , 0
       0    .035       0     100      .1       0   243.2    .035       0
  453.97    .045       0   501.3      .1       0   603.2    .035       0
   793.2     .04       0  911.44    .035       0
#XS Ineff= 1 ,-1
  669.05  839.541559.873
Permanent Ineff=
       F
Bank Sta=453.97,501.3
XS Rating Curve= 0 ,0
Exp/Cntr=0.3,0.1

Type RM Length L Ch R = 1 ,897     ,340.3,342.5,350.1
XS GIS Cut Line= 2
     2023587.566      147883.623     2024022.384      148489.419
#Sta/Elev= 30
       0 1595.19      72 1597.46    81.8 1598.03    88.3 1597.22   104.7 1597.54
   127.6 1595.76   130.8 1593.62   134.1 1588.68   140.6  1576.7   147.2 1565.88
   150.4 1561.98   153.7 1559.34   160.3  1555.5   166.8  1553.6   179.9 1552.03
   189.7 1552.92   212.6 1552.94   310.7 1552.39   359.8 1552.58   400.5  1550.5
   408.8 1549.37   450.5  1550.7   464.4 1554.71   477.5 1554.01   542.9 1555.26
   585.4 1556.51   605.1 1557.85   667.2 1570.24   703.2 1573.56   745.7 1575.85
#Mann= 7 ,-1 , 0
       0    .035       0      72      .1       0   212.6    .035       0
   310.7      .1       0   400.5    .045       0   450.5      .1       0
   542.9    .035       0
#XS Ineff= 1 ,-1
  539.83  632.66 1559.47
Permanent Ineff=
       F
Bank Sta=400.5,450.5
XS Rating Curve= 0 ,0
Exp/Cntr=0.5,0.3

Type RM Length L Ch R = 1 ,555     ,88.5,87.3,85.1
XS GIS Cut Line= 6
2023376.11398596148142.2204418172023474.22422179148246.462567376
2023532.77937177 148325.403792042023575.47164808148314.503636387
2023661.12586104148419.0608813882023776.27255974148576.905010096
#Sta/Elev= 30
       01568.592   4.8321570.143  14.4061574.949  19.1931576.028  51.6361579.132
  86.675  1581.2  91.1811580.377 109.2021575.231  119.721569.337 132.8691560.676
 139.8321557.141 149.1351555.698 157.3051552.159 165.4741550.738   172.61548.024
 176.7731547.161 182.012 1547.03 193.7381547.129   203.11548.045 226.7471551.328
 233.608 1551.24 241.4381550.561 269.3991551.064 348.8941551.369 411.5731552.477
 462.9151554.369 505.1811556.761 560.6011561.933 587.3651563.566 616.0431565.999
#Mann= 3 ,-1 , 0
       0    .035       0   172.6    .045       0   203.1    .035       0
#XS Ineff= 3 ,-1
       0  165.04 1549.42  218.34   308.6 1549.24  348.14   577.3 1557.63
Permanent Ineff=
       F       F       F
Bank Sta=172.6,203.1
XS Rating Curve= 0 ,0
Exp/Cntr(USF)=0,0
Exp/Cntr=0.5,0.3

Type RM Length L Ch R = 1 ,468     ,225,223.9,222.1
XS GIS Cut Line= 2
     2023330.609       148220.04     2023689.984      148617.609
#Sta/Elev= 30
       0 1558.83    29.4 1556.92    71.9 1553.49   111.1 1551.18   124.2 1551.16
   127.4  1550.8   130.7 1550.07   137.2 1547.52   143.8 1546.67   153.6 1546.48
   163.4 1547.28   169.9 1546.55   173.2 1546.52   176.5 1547.04   177.7 1547.49
     183 1549.41   186.3 1550.05   205.9 1551.19   228.8 1550.83   287.6 1551.27
   307.2 1551.09   352.9 1551.89   431.4 1551.81   454.2 1552.43     464  1553.5
   470.6 1554.74   490.2 1561.15     500 1563.36   526.1 1567.64   535.9  1568.7
#Mann= 3 ,-1 , 0
       0    .035       0   137.2    .045       0   177.7    .035       0
#XS Ineff= 3 ,-1
   87.68  130.66 1548.42  183.09  252.72 1548.53  403.15  511.46 1558.08
Permanent Ineff=
       F       F       F
Bank Sta=137.2,177.7
XS Rating Curve= 0 ,0
Exp/Cntr=0.5,0.3

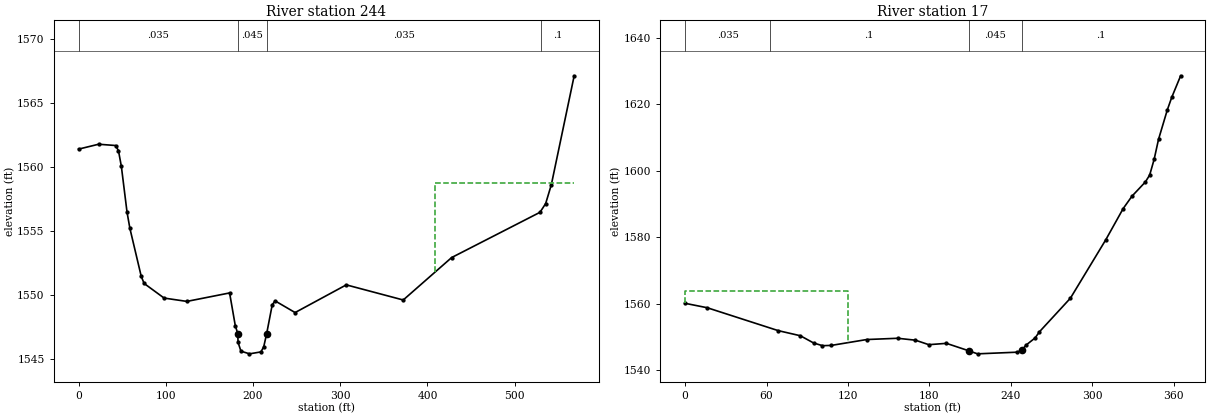
Type RM Length L Ch R = 1 ,244     ,205.8,227,238.9
XS GIS Cut Line= 2
     2023140.447      148358.466     2023544.151      148758.234
#Sta/Elev= 30
       0 1561.41    22.9 1561.79    42.4 1561.69    45.7 1561.28      49 1560.06
    55.5 1556.49    58.8 1555.22    71.8 1551.48    75.1 1550.93      98 1549.79
   124.1 1549.53   173.1 1550.19   179.6 1547.65  182.46 1547.02   182.8 1546.34
   186.1 1545.65   195.9 1545.44     209 1545.59   212.2 1545.98   215.5 1546.98
     222 1549.27   225.3 1549.57   248.2 1548.66   306.9 1550.82   372.2 1549.64
   427.7 1552.95     529 1556.48   535.5 1557.16     542 1558.63   568.2 1567.13
#Mann= 4 ,-1 , 0
       0    .035       0  182.46    .045       0   215.5    .035       0
     530      .1       0
#XS Ineff= 2 , 0
                          408.31          1558.8
Permanent Ineff=
       F       F
Bank Sta=182.46,215.5
XS Rating Curve= 0 ,0
Exp/Cntr=0.3,0.1

Type RM Length L Ch R = 1 ,17      ,0,16.6,35.2
XS GIS Cut Line= 4
     2023103.989      148380.167     2023087.319      148419.245
     2023106.267       148633.69     2023069.462      148734.384
#Sta/Elev= 30
       0 1560.07    16.3 1558.74    68.6 1551.84    84.9  1550.3    94.7 1548.11
   101.2 1547.31   107.7 1547.39   133.8 1549.16   156.6 1549.54   169.7 1548.96
   179.5 1547.61   192.5 1548.01   208.8 1545.79   215.4 1544.85   244.7 1545.35
     248 1545.96   251.2  1547.5   257.8 1549.64     261 1551.49   283.8 1561.61
   309.8 1579.17   322.7 1588.63   329.2 1592.37     339 1596.62   342.2 1598.72
   345.5 1603.48   348.7 1609.45   355.2 1618.36   358.5 1622.18     365 1628.62
#Mann= 4 ,-1 , 0
       0    .035       0   62.49      .1       0   208.8    .045       0
     248      .1       0
#XS Ineff= 2 , 0
          119.77 1563.84
Permanent Ineff=
       F       F
Bank Sta=208.8,248
XS Rating Curve= 0 ,0
Exp/Cntr=0.3,0.1
LCMann Table=0

Chan Stop Cuts=-1
Use User Specified Reach Order=0
Composite Channel Slope=5